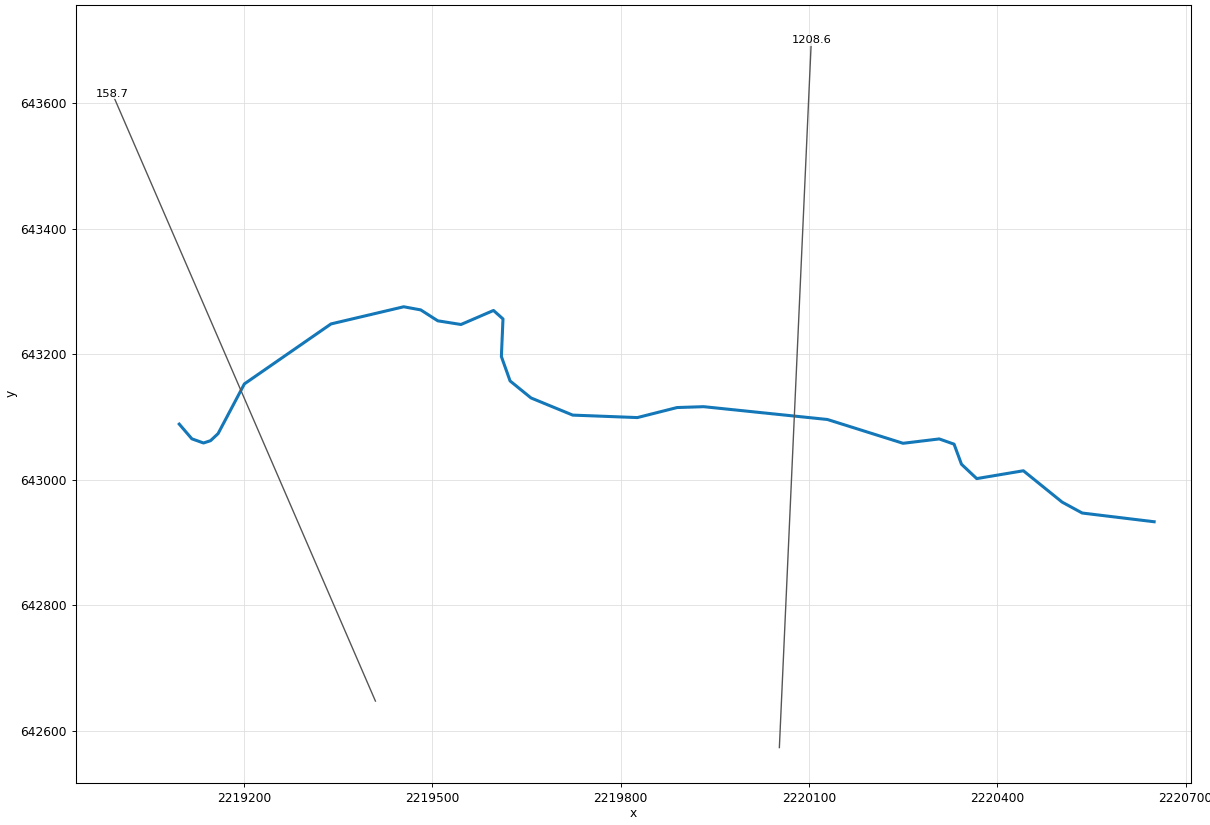
--- COLDRN.prj (project) ---

Proj Title=COLDRN
Current Plan=p01
Geom File=g01
Flow File=f01
Plan File=p01
DSS Export Rating Curves=0
DSS Export Rating Curve Sorted=0
DSS Export Volume Flow Curves=0
DXF OffsetX=0
DXF OffsetY=0
DXF ScaleX=0
DXF ScaleY=0

--- COLDRN.p01 (plan) ---

Plan Title=Floodplain
Program Version=4.00
Geom File=g01
Flow File=f01
K Sum by GR=0
Std Step Tol=0.01
Critical Tol=0.01
Num of Std Step Trials=20
Max Error Tol=0.3
Flow Tol Ratio=0.001
Split Flow NTrial=30
Split Flow Tol=0.02
Split Flow Ratio=0.02
Log Output Level=0
Friction Slope Method=1
Unsteady Friction Slope Method=2
Unsteady Bridges Friction Slope Method=1
Global Log Level=0
CheckData=False
Run HTab=0
Run UNet=0
Run PostProcess=0
UNET Theta=0
UNET Theta Warmup=0
UNET ZTol=0
UNET ZSATol=0
UNET MxIter=0
UNET MaxInSteps=0
UNET DtIC=0
UNET DtMin=0
UNET MaxCRTS=0
UNET WFStab=0
UNET SFStab=0
UNET WFX=0
UNET SFX=0
UNET DSS MLevel=0
UNET DZMax Abort=0
UNET Convert EG Bridges=0
UNET Use Existing IB Tables=0
UNET Froude Limit=0
UNET Froude Power=0
Write IC File=0
Echo Input=False
Echo Output=False
Write Detailed=0

--- COLDRN.f01 (steady flow) ---

Flow Title=Flow
Program Version=4.00
Number of Profiles=1
Profile Names=P100yr
River Rch & RM=COLDRN,Main      ,1208.6
319.5913
River Rch & RM=COLDRN,Main      ,1208.6
257.7247
River Rch & RM=COLDRN,Main      ,158.7
339.4964
River Rch & RM=COLDRN,Main      ,158.7
334.5036
River Rch & RM=COLDRN,Main      ,158.7
326.0300
Boundary for River Rch & Prof#=COLDRN,Main      ,1
Up Type=0
Dn Type=3
Dn Slope=0.01096

--- COLDRN.g01 (geometry) ---

Geom Title=Geometry
Program Version=4.00

River Reach=COLDRN     ,Main
Reach XY= 30
     2220649.973      642933.206     2220535.390      642947.095
     2220503.445      642964.456     2220441.640      643014.456
     2220367.334      643001.956     2220343.029      643024.872
     2220331.223      643056.817     2220307.612      643065.150
     2220249.973      643058.206     2220129.475      643096.130
     2219932.265      643116.539     2219889.904      643115.151
     2219826.709      643099.178     2219723.722      643103.102
     2219657.265      643130.428     2219623.931      643157.512
     2219610.043      643196.400     2219612.600      643256.325
     2219597.499      643269.826     2219545.679      643247.455
     2219508.654      643253.345     2219481.570      643270.706
     2219454.434      643275.698     2219338.633      643248.371
     2219200.619      643152.817     2219158.727      643073.631
     2219146.740      643062.397     2219135.512      643058.685
     2219116.940      643065.326     2219096.848      643088.761

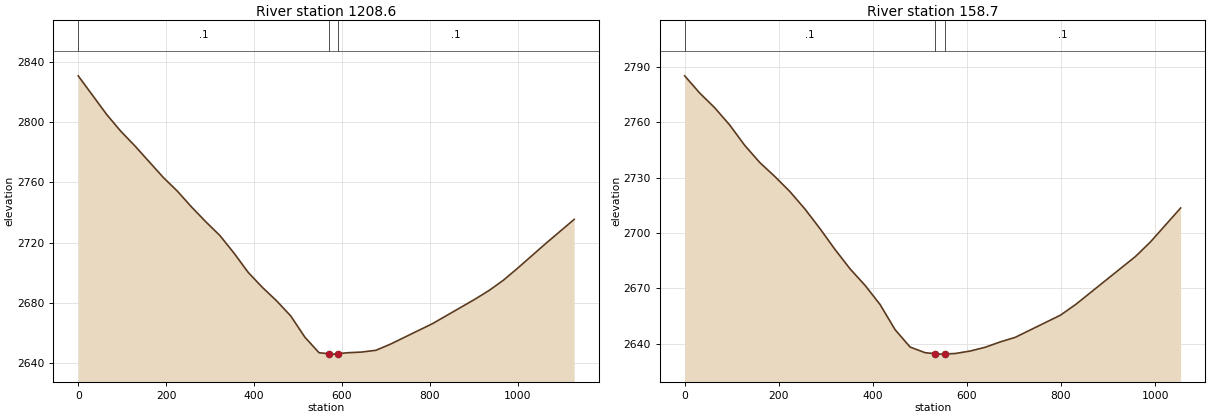
Type RM Length L Ch R = 1 ,1208.6,1028.9,1049.9,1059.7
XS GIS Cut Line= 2
     2220052.902      642573.442     2220103.827      643700.756
#Sta/Elev= 30
       0 2830.89    64.5 2805.29    96.7 2794.12   129.0 2784.32   193.4 2763.40
   225.7 2754.21   257.9 2743.71   290.2 2733.91   322.4 2724.73   354.7 2712.97
   386.9 2700.19   419.1 2690.26   451.4 2681.33   483.6 2671.28   515.9 2657.12
   548.1 2646.79   570.4 2646.17   580.4 2645.89   590.4 2646.17   612.6 2646.80
   644.8 2647.26   677.1 2648.42   709.3 2652.36   806.0 2666.12   902.8 2682.39
   935.0 2688.22   967.3 2694.98   999.5 2702.91  1064.0 2719.46  1128.5 2735.44
#Mann= 3 , 0 , 0
       0     0.1       0   570.4   0.045       0   590.4     0.1       0
Bank Sta=570.4,590.4
Exp/Cntr=0.3,0.1

Type RM Length L Ch R = 1 ,158.7,189.7,158.7,124.5
XS GIS Cut Line= 2
     2219409.383      642647.516     2218990.402      643615.108
#Sta/Elev= 30
       0 2785.08    32.0 2775.75    63.9 2767.78    95.9 2758.40   127.8 2747.38
   159.8 2738.10   191.7 2730.57   223.7 2722.42   255.6 2712.99   287.6 2702.36
   319.5 2691.10   351.5 2680.59   383.4 2671.65   415.4 2661.26   447.3 2647.64
   479.3 2638.21   511.2 2635.15   533.2 2634.62   543.2 2634.38   553.2 2634.48
   575.1 2634.71   607.1 2636.06   639.0 2638.10   671.0 2641.00   702.9 2643.48
   798.8 2655.46   830.8 2661.16   958.6 2687.29   990.5 2695.20  1054.4 2713.51
#Mann= 3 , 0 , 0
       0     0.1       0   533.2   0.045       0   553.2     0.1       0
Bank Sta=533.2,553.2
Exp/Cntr=0.3,0.1