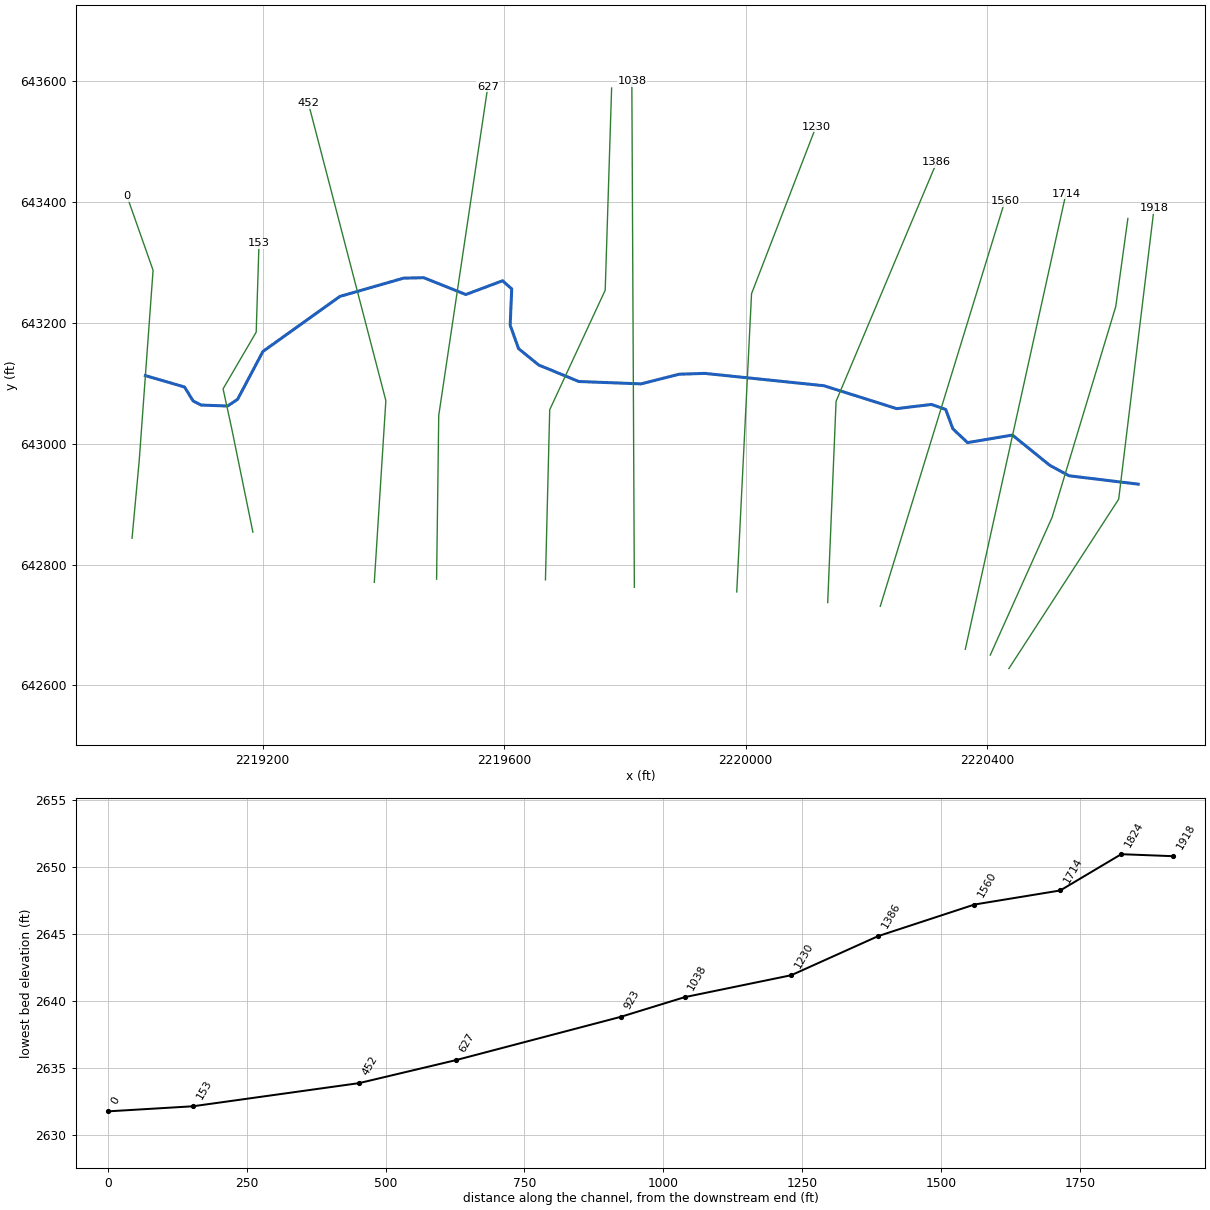
--- COLDRN.prj (project) ---

Proj Title=COLDRN
Current Plan=p01
Default Exp/Contr=0,0
English Units
Geom File=g01
Flow File=f01
Plan File=p01
BEGIN DESCRIPTION:
----------MODEL BY WOOD PLC 2022----------
AFH study
Randolph County, WV
HEC-RAS Version: RAS 6.2
Vertical Datum: NAVD88
Projection: NAD 1983 StatePlane West Virginia S FIPS 4702 (US Feet)
Terrain: 1-meter LIDAR (FEMA Region III 3DEP collected 2016-2018)
Land Use: 2019 NLCD
Hydrologic Method:
WV SIR2010-5033 regression equations
Additional Model Notes:
Downstream boundary is outside this county.
END DESCRIPTION:
DSS Export Rating Curves= 0
DSS Export Rating Curve Sorted= 0
DSS Export Volume Flow Curves= 0
DXF OffsetX= 0
DXF OffsetY= 0
DXF ScaleX= 0
DXF ScaleY= 0

--- COLDRN.p01 (plan) ---

Plan Title=Floodplain
Program Version=6.20
Short Identifier=Floodplain
Geom File=g01
Flow File=f01
Subcritical Flow
K Sum by GR= 0
Std Step Tol= 0.01
Critical Tol= 0.01
Num of Std Step Trials= 20
Max Error Tol= 0.3
Flow Tol Ratio= 0.001
Split Flow NTrial= 30
Split Flow Tol= 0.02
Split Flow Ratio= 0.02
Log Output Level= 0
Friction Slope Method= 1
Unsteady Friction Slope Method= 2
Unsteady Bridges Friction Slope Method= 1
Parabolic Critical Depth
Global Vel Dist= 0 , 0 , 0
Global Log Level= 0
CheckData=True
Encroach Param=-1 ,0,0, 0
Mapping Interval=1HOUR
Computation Time Step Use Courant=        0
Computation Time Step Use Time Series=    0
Computation Time Step Count To Double=0
Computation Time Step Max Doubling=0
Computation Time Step Max Halving=0
Computation Time Step Residence Courant=0
Run HTab= 0
Run UNet= 0
Run Sediment= 0
Run PostProcess= 0
Run WQNet= 0
Run RASMapper=-1
UNET Theta= 0
UNET Theta Warmup= 0
UNET ZTol= 0
UNET ZSATol= 0
UNET MxIter= 0
UNET Max Iter WO Improvement= 0
UNET MaxInSteps= 0
UNET DtIC= 0
UNET DtMin= 0
UNET MaxCRTS= 0
UNET WFStab= 0
UNET SFStab= 0
UNET WFX= 1
UNET SFX= 1
UNET Gravity=32.174
UNET 1D Methodology=Finite Difference
UNET DSS MLevel= 1
UNET Pardiso=0
UNET DZMax Abort= 0
UNET Use Existing IB Tables= 0
UNET Froude Reduction=False
UNET Froude Limit= 0
UNET Froude Power= 0
UNET D1 Cores= 0
UNET WindReference=Eulerian
UNET WindDragFormulation=Hsu (1988)
UNET D2 Coriolis=0
UNET D2 Cores= 0
UNET D2 Theta= 1
UNET D2 Theta Warmup= 1
UNET D2 Z Tol= 0.01
UNET D2 Volume Tol= 0.01
UNET D2 Max Iterations= 20
UNET D2 Equation= 0
UNET D2 RampUpFraction=0.1
UNET D2 TimeSlices= 1
UNET D2 Turbulence Formulation=Non-Conservative (original)
UNET D2 Eddy Viscosity=0.3
UNET D2 Transverse Eddy Viscosity=0.1
UNET D2 Smagorinsky Mixing=0
UNET D2 BCVolumeCheck=0
UNET D2 Cores=0
UNET D2 SolverType=PARDISO (Direct)
UNET D2 Minimum Iterations= 2147483647
UNET D2 Maximum Iterations= 2147483647
UNET D2 Restart Number= 10
UNET D2 Relaxation Coeff=1.3
UNET D2 SOR Precondition Iterations= 10
UNET D2 ILUT Maximum Fill= 8
UNET D2 ILUT Tolerance=1E-08
UNET D1D2 MaxIter= 0
UNET D1D2 ZTol=0.01
UNET D1D2 QTol=0.1
UNET D1D2 MinQTol=1
Write IC File= 0
Write IC File at Fixed DateTime=0
Write IC File at Sim End=0
Echo Input=False
Echo Parameters=False
Echo Output=False
Write Detailed= 0
HDF Write Warmup=0
HDF Write Time Slices=0
HDF Flush=0
HDF Compression= 1
HDF Chunk Size= 1
HDF Spatial Parts= 1
HDF Use Max Rows=0
HDF Fixed Rows= 1
Calibration Method= 0
Calibration Iterations= 20
Calibration Max Change=0.05
Calibration Tolerance=0.2
Calibration Maximum=1.5
Calibration Minimum=0.5
Calibration Optimization Method= 1
WQ AD Non Conservative
WQ ULTIMATE=-1
WQ Max Comp Step=1HOUR
WQ Output Interval=15MIN
WQ Output Selected Increments= 0
WQ Output face flow=0
WQ Output face velocity=0
WQ Output face area=0
WQ Output face dispersion=0
WQ Output cell volume=0
WQ Output cell surface area=0
WQ Output cell continuity=0
WQ Output cumulative cell continuity=0
WQ Output face conc=0
WQ Output face dconc_dx=0
WQ Output face courant=0
WQ Output face peclet=0
WQ Output face adv mass=0
WQ Output face disp mass=0
WQ Output cell mass=0
WQ Output cell source sink temp=0
WQ Output nsm pathways=0
WQ Output nsm derived pathways=0
WQ Create Restart=0
WQ Fixed Restart=0
WQ System Summary=0
WQ Write To DSS=0
Sorting and Armoring Iterations= 10
XS Update Threshold= 0.02
Bed Roughness Predictor= 0
Hydraulics Update Threshold= 0.02
Energy Slope Method= 1
Volume Change Method= 1
Sediment Retention Method= 0
Sediment TS Multiplier= 1
Warm Up Method= 0
XS Weighting Method= 0
Number of US Weighted Cross Sections= 1
Number of DS Weighted Cross Sections= 1
Upstream XS Weight=0
Main XS Weight=1
Downstream XS Weight=0
Number of DS XS's Weighted with US Boundary= 1
Upstream Boundary Weight= 1
Weight of XSs Associated with US Boundary= 0
Number of US XS's Weighted with DS Boundary= 1
Downstream Boundary Weight= 0.5
Weight of XSs Associated with DS Boundary= 0.5
Percentile Method= 0
Sediment Output Level= 3
Mass or Volume Output= 0
Output Increment Type= 1
Profile and TS Output Increment= 1
Transport Output Increment 1
XS Output Flag= 0
XS Output Increment= 10
Read HDF5 Sediment Hotstart= 0
Sediment Hotstart Type= 0
Write Gradation File= 0
Read Gradation Hotstart= 0
Write HDF5 File= 1
Write Binary Output= 1
Write DSS Sediment File= 0
DSS Sediment Output Type= 1
SV Curve= 0
Specific Gage Flag= 0
Subcell Erosion Methods= 0
Subcell Deposition Methods= 0
Advection Scheme= 1
Matrix Solver= 0
Implicit Weighting Factor= 1
Maximum Outer Loop Convergence Iterations= 5
Convergence Maximum Absolute= 0.001
Convergence RMSE= 0.0001
Grain Fractions Max Abs Error= 0.001
Max Subgrid Regions= 1
Max Subgrid Length Scale= 3.402823E+38
Initial Layer Thickness= 3.402823E+38
Min Layer Thickness= 3.402823E+38
Max Layer Thickness= 3.402823E+38
Number of Layers= 5

--- COLDRN.f01 (steady flow) ---

Flow Title=Flow
Program Version=6.20
Number of Profiles= 1
Profile Names=P100yr
River Rch & RM=COLDRN,Main            ,1918
     344
River Rch & RM=COLDRN,Main            ,153
     429
Boundary for River Rch & Prof#=COLDRN,Main            , 1
Up Type= 0
Dn Type= 1
Dn Known WS=2633.66
DSS Import GetInterval= 0
DSS Import GetPeak= 0
DSS Import FillOption= 0

--- COLDRN.g01 (geometry) ---

Geom Title=Geometry
Program Version=6.20

River Reach=COLDRN          ,Main
Reach XY= 30
     2220649.973642933.2060000152220535.39000003642947.094999999
2220503.44500001      642964.4562220441.64000002      643014.456
2220367.33399999643001.9560000152220343.02899998643024.871999994
     2220331.223643056.817000002     2220307.612643065.150000006
2220249.97300003643058.2060000152220129.47500001643096.129999995
     2219932.265643116.539000005     2219889.904643115.151000008
2219826.70900005643099.178000018     2219723.722643103.101999998
2219657.26500003643130.4280000032219623.93100001643157.511999995
2219610.04299998643196.4000000212219612.60000001643256.325000018
2219597.49900004643269.8260000052219536.55800003643247.052000016
2219466.95099999643274.883000016     2219433.654643274.178000003
2219328.08100002643243.9160000092219200.61900003643152.817000017
2219158.72700001643073.6310000122219142.23944774643062.511180609
2219098.31335454643064.1424109342219085.09258042643070.867135003
2219070.81308146643094.0465506022219006.03763474643112.858089169

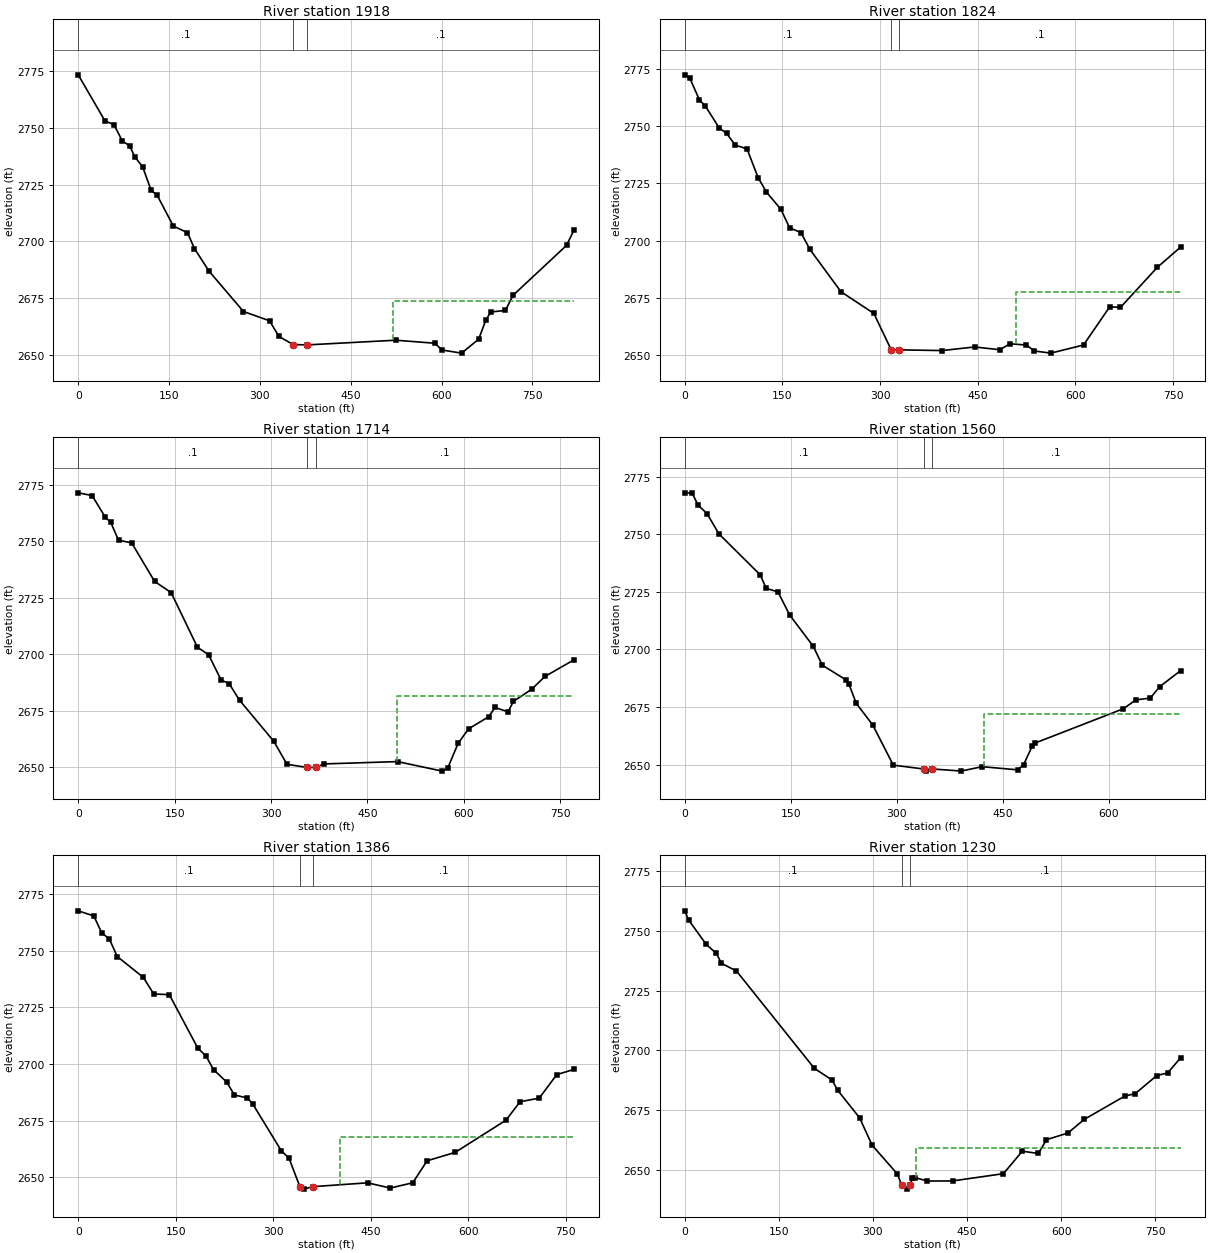
Type RM Length L Ch R = 1 ,1918    ,94.9,93.9,94
BEGIN DESCRIPTION:
IFA needed to wet channel
END DESCRIPTION:
XS GIS Cut Line= 3
2220435.82045622642628.0503007342220617.62335236642908.384378145
2220676.19685458643389.725107331
#Sta/Elev= 30
       0 2773.33    44.3 2752.99    58.9 2751.43    72.9  2744.2    84.9 2742.12
    93.6 2737.13   106.2 2732.93   120.5 2722.46   130.1 2720.45   157.2  2706.7
   180.4 2703.85     192 2696.81   215.9 2686.93   272.9 2669.11     316 2665.03
   331.5 2658.12   355.1 2654.56   355.2 2654.56  377.782654.409   524.3 2656.48
   588.8 2655.15   600.9 2652.15   633.1 2650.79   661.3 2656.93   673.4 2665.52
   681.5 2668.92   705.6 2669.58   717.9 2676.19   806.4 2698.23     819 2705.13
#Mann= 3 ,-1,0
       0      .1       0   355.1    .045       0  377.78      .1       0
#XS Ineff= 2 , 0
                          519.13         2673.61
Permanent Ineff=
       F       F
Bank Sta=355.2,377.78
XS Rating Curve= 0 ,0
Exp/Cntr(USF)=0,0
Exp/Cntr=0.3,0.1

Type RM Length L Ch R = 1 ,1824    ,109.5,109.8,111.5
XS GIS Cut Line= 4
2220404.98652131642650.3275709352220507.30328491642878.166962044
 2220612.7844845643227.3097326782220632.82591242643372.873788108
#Sta/Elev= 30
       0 2772.28     7.6 2771.01    22.7 2761.31    31.8 2758.64      53 2749.11
    64.5  2746.7    77.7 2741.62    95.7 2740.02   112.7 2727.46   125.6 2721.14
   147.8 2713.61     161  2705.6   178.5 2703.49   192.2 2696.19   239.9 2677.73
   290.5 2668.23   317.1 2652.37  328.352652.372     395 2652.06   445.1 2653.63
   483.9 2652.42   499.4 2655.02   524.5 2654.46     537 2651.88   562.1 2650.94
   612.3 2654.48   652.7 2671.19   668.9 2670.84   725.6 2688.33   761.4 2697.19
#Mann= 3 ,-1,0
       0      .1       0   317.1    .045       0  328.35      .1       0
#XS Ineff= 2 , 0
                          508.56         2677.68
Permanent Ineff=
       F       F
Bank Sta=317.1,328.35
XS Rating Curve= 0 ,0
Exp/Cntr(USF)=0,0
Exp/Cntr=0.3,0.1

Type RM Length L Ch R = 1 ,1714    ,153.7,154.3,152.5
XS GIS Cut Line= 2
2220363.63044342642659.9432267752220530.18317059643413.594317244
#Sta/Elev= 30
       0 2771.55    21.6 2770.35    42.2 2760.71    50.4  2758.6    62.7 2750.56
    83.2 2749.37   118.9 2732.29   144.6 2727.35   185.6 2703.11   202.8 2699.85
   222.5 2688.55   234.8 2687.03   251.2  2679.6   304.4 2661.44   324.9 2651.25
  356.642649.855     370 2649.86   382.2 2651.42   496.9 2652.45   566.6 2648.23
   574.8 2649.41   591.2 2660.52   607.5 2666.97     639 2672.35   648.5 2676.43
     669 2674.51   677.2 2679.12   705.9 2684.53   726.3 2690.17   771.8 2697.58
#Mann= 3 ,-1,0
       0      .1       0  356.64    .045       0     370      .1       0
#XS Ineff= 2 , 0
                          495.45         2681.74
Permanent Ineff=
       F       F
Bank Sta=356.64,370
XS Rating Curve= 0 ,0
Exp/Cntr(USF)=0,0
Exp/Cntr=0.3,0.1

Type RM Length L Ch R = 1 ,1560    ,175.1,173.4,172.2
XS GIS Cut Line= 2
2220222.84802668642731.0079345972220429.11535916643401.685548596
#Sta/Elev= 30
       0 2767.96    10.6 2767.85      19 2762.57    31.6 2758.98    48.3  2750.2
   106.9 2732.35   115.3 2726.51     132 2724.95   148.7 2714.88     182 2701.31
   194.8 2693.13   228.3 2686.79   232.4 2684.92   242.8 2676.57   265.9  2667.3
   295.2 2649.77   338.2 2648.11   342.1 2647.18   349.6 2648.13   391.5 2647.22
   420.8 2649.11     471 2647.74   479.4 2649.84   491.9  2658.2   496.1 2659.41
   620.5 2674.23   638.4 2678.08   658.9 2678.91   672.1 2683.83   701.7  2690.8
#Mann= 3 ,-1,0
       0      .1       0   338.2    .045       0   349.6      .1       0
#XS Ineff= 2 , 0
                          424.04         2671.77
Permanent Ineff=
       F       F
Bank Sta=338.2,349.6
XS Rating Curve= 0 ,0
Exp/Cntr(USF)=0,0
Exp/Cntr=0.3,0.1

Type RM Length L Ch R = 1 ,1386    ,152.2,156.3,158.6
XS GIS Cut Line= 3
2220135.80482367642737.222104195 2220149.6842176643070.327558546
2220316.23694478643465.890285587
#Sta/Elev= 30
       0 2767.51      24 2765.25      36 2757.86      48 2755.03      60 2747.37
     100  2738.2   116.1 2730.87   140.1 2730.54   184.1 2706.87   196.1 2703.68
   208.1 2697.49   228.2 2692.05   240.2 2686.33   260.2    2685   268.2 2682.44
   312.2 2661.78   324.2 2658.44   340.8 2645.93   346.6 2644.82   360.4  2645.9
     445  2647.6   479.7 2645.29   514.4 2647.62   536.5 2657.31   579.5    2661
   657.7  2675.2   679.5 2683.36   708.9 2684.92   735.8 2695.29   762.6 2697.62
#Mann= 3 ,-1,0
       0      .1       0   340.8    .045       0   360.4      .1       0
#XS Ineff= 2 , 0
                          402.19          2667.7
Permanent Ineff=
       F       F
Bank Sta=340.8,360.4
XS Rating Curve= 0 ,0
Exp/Cntr(USF)=0,0
Exp/Cntr=0.3,0.1

Type RM Length L Ch R = 1 ,1230    ,191.7,191.9,192.1
XS GIS Cut Line= 3
2219985.20140071642754.7994140362220009.70589817643248.429529462
2220116.31845454643524.487697073
#Sta/Elev= 30
       0 2758.44     6.4 2754.56    34.4 2744.34    50.4 2740.65    58.5 2736.46
    82.5 2733.25   206.6 2692.47   234.7  2687.6   243.8  2683.3   278.7 2671.75
   298.7 2660.28   338.8 2648.26  345.842643.542   354.8  2641.9   358.8 2643.53
   362.8 2646.37   366.8 2646.76   386.7 2645.28   426.9 2645.33   507.9 2648.37
   537.9 2657.78   563.6 2656.83   576.5  2662.6   610.8 2665.42   636.5 2671.08
   700.9 2680.82     718 2681.91   752.3 2689.48   769.5 2690.55   790.2 2696.89
#Mann= 3 ,-1,0
       0      .1       0  345.84    .045       0   358.8      .1       0
#XS Ineff= 2 , 0
                          367.94         2659.03
Permanent Ineff=
       F       F
Bank Sta=345.84,358.8
XS Rating Curve= 0 ,0
Exp/Cntr(USF)=0,0
Exp/Cntr=0.3,0.1

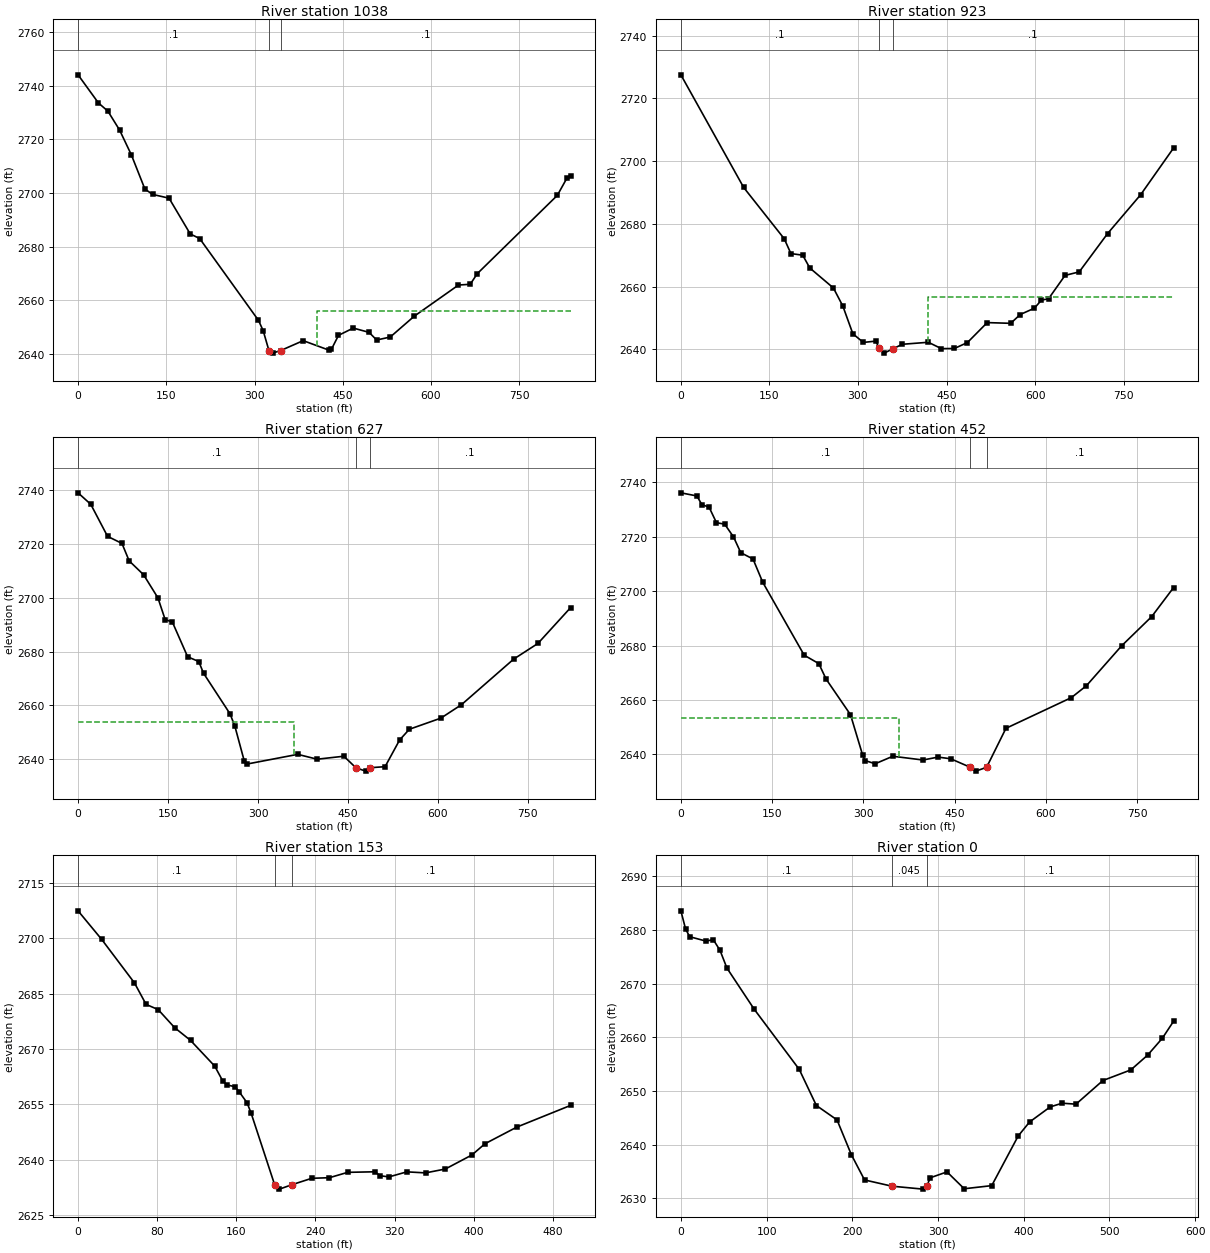
Type RM Length L Ch R = 1 ,1038    ,119.2,115,109.3
XS GIS Cut Line= 2
 2219815.6610547642762.5261565532219811.49723652643599.916257073
#Sta/Elev= 30
       0 2743.99    34.7 2733.49    50.7 2730.46    70.7 2723.37    90.7 2714.12
   113.6 2701.43   126.7 2699.42   154.7 2698.01   190.7 2684.68   206.7 2682.98
   306.7 2652.47   314.7 2648.63   324.5 2641.19   330.7 2640.26   344.4 2641.22
   382.7 2644.91   426.7 2641.36   430.7 2641.68   442.7 2646.88   467.8  2649.6
   494.7    2648   507.6 2645.15   530.7 2646.26   571.3 2653.99   646.7 2665.64
   666.7 2665.92   678.5 2669.85   814.7 2699.06   830.7 2705.37   837.4 2706.17
#Mann= 3 ,0,0
       0      .1       0   324.5    .045       0   344.4      .1       0
#XS Ineff= 2 , 0
                          405.78         2655.97
Permanent Ineff=
       F       F
Bank Sta=324.5,344.4
XS Rating Curve= 0 ,0
Exp/Cntr(USF)=0,0
Exp/Cntr=0.3,0.1

Type RM Length L Ch R = 1 ,923     ,287.9,296.3,294.1
XS GIS Cut Line= 4
2219668.45501057642774.8383952342219675.52279304643056.371730186
2219767.40396511643254.2696392742219778.00563881643588.811342732
#Sta/Elev= 30
       0  2727.5   106.4 2691.59   175.1 2675.24   186.4 2670.52   206.4 2670.01
   218.4 2665.93   258.4 2659.55   274.4 2653.78   291.3 2644.98     309  2642.2
   330.7 2642.63   335.4 2640.28   344.3 2638.79   359.2 2640.17   375.1 2641.61
   419.2 2642.25   441.3 2640.22   463.3 2640.27   485.4 2642.16   518.9 2648.52
   558.7 2648.29   574.8 2651.09   598.8 2653.11   610.8 2655.69   622.8 2656.12
   650.8 2663.57   674.8 2664.69   722.8 2676.89   778.8 2689.27   834.5 2704.15
#Mann= 3 ,-1,0
       0      .1       0   335.4    .045       0   359.2      .1       0
#XS Ineff= 2 , 0
                          418.77         2656.83
Permanent Ineff=
       F       F
Bank Sta=335.4,359.2
XS Rating Curve= 0 ,0
Exp/Cntr(USF)=0,0
Exp/Cntr=0.3,0.1

Type RM Length L Ch R = 1 ,627     ,168.5,174.5,178.8
XS GIS Cut Line= 3
2219488.22655765642776.0163589782219491.76044888 643046.94802023
2219573.03994726643591.167270221
#Sta/Elev= 30
       0 2739.03    21.2 2734.76    49.2 2722.85    73.2 2720.22    85.2 2713.73
   109.2 2708.59   133.2 2699.96   145.2  2691.9   157.2    2691   182.7 2678.07
   201.2 2676.31   209.2 2671.95   253.2 2656.91   261.2 2652.44   277.3 2639.15
   281.3 2638.18   366.2  2641.8   398.6 2639.99   443.1  2641.1   463.3 2636.78
   479.5 2635.56  486.09 2636.82   511.8 2637.21   536.1 2647.16   552.3 2651.13
   604.8 2655.26   639.2 2660.27   726.2 2677.21   766.6 2683.03   821.2 2696.38
#Mann= 3 ,-1,0
       0      .1       0   463.3    .045       0  486.09      .1       0
#XS Ineff= 2 , 0
          359.57 2653.93
Permanent Ineff=
       F       F
Bank Sta=463.3,486.09
XS Rating Curve= 0 ,0
Exp/Cntr(USF)=0,0
Exp/Cntr=0.3,0.1

Type RM Length L Ch R = 1 ,452     ,298.4,299.1,303.3
XS GIS Cut Line= 3
2219385.07493717642770.837516326 2219404.1984772643071.423489145
 2219275.9064796 643563.77535015
#Sta/Elev= 30
       0 2736.17    26.4 2735.02    34.4 2731.86    46.4 2730.89    58.5 2725.19
      72 2724.65    86.5 2719.98    98.5 2714.16   118.6 2711.84   134.6 2703.28
   202.8 2676.46   226.8 2673.38   238.8 2667.68   278.9 2654.59   298.9 2639.72
     303 2637.72   319.5 2636.55   348.5 2639.31   398.1 2637.93   422.9    2639
   443.7 2638.38   475.8 2635.26   484.9 2633.84   502.7 2635.24   534.5 2649.58
     642 2660.86   666.8 2665.24   724.6 2679.89   774.2 2690.67     810  2701.3
#Mann= 3 ,-1,0
       0      .1       0   475.8    .045       0   502.7      .1       0
#XS Ineff= 2 , 0
          358.12 2653.31
Permanent Ineff=
       F       F
Bank Sta=475.8,502.7
XS Rating Curve= 0 ,0
Exp/Cntr(USF)=0,0
Exp/Cntr=0.3,0.1

Type RM Length L Ch R = 1 ,153     ,150.7,153.3,157.1
XS GIS Cut Line= 5
2219184.03773896642853.8072615142219148.64295053643026.759362203
2219134.66595676643090.956225949 2219189.4955968643184.785539254
2219194.17379231643331.823306503
#Sta/Elev= 30
       0 2707.36    23.9 2699.63      57 2687.88    68.8 2682.06      81 2680.65
    97.6 2675.78   113.7 2672.33   138.2 2665.36   146.3 2661.34   150.4 2660.31
   158.6 2659.79   162.7  2658.5   170.8 2655.48   174.9  2652.7  198.72 2633.31
   203.6 2632.11   215.9 2633.28   236.3 2635.04   254.1  2635.2   272.6 2636.65
   300.4  2636.8     305 2635.74   314.3 2635.42   332.4 2636.78   351.3  2636.5
   371.3 2637.55   398.2 2641.35   411.3 2644.37   443.6 2648.89     498 2654.76
#Mann= 3 ,0,0
       0      .1       0  198.72    .045       0   215.9      .1       0
Bank Sta=198.72,215.9
XS Rating Curve= 0 ,0
Exp/Cntr=0.3,0.1

Type RM Length L Ch R = 1 ,0       ,162.7,182.6,189.3
XS GIS Cut Line= 4
2218983.93199746642843.6610469892218995.72988584642971.325910486
2219018.76151076643287.1881951182218975.61712295643409.704932345
#Sta/Elev= 30
       0 2683.55     5.5 2680.16    10.3 2678.73    29.6  2677.9    37.7 2678.21
    45.7 2676.18    53.7  2672.9    85.5 2665.24   138.1 2654.03   158.1  2647.3
   182.2 2644.62   198.9 2638.15   214.3 2633.44   246.2 2632.28   282.5 2631.73
   286.7 2632.27   291.1 2633.85   310.5 2634.94   330.6  2631.8   362.7 2632.38
   393.6 2641.63   406.8 2644.22   430.9 2647.04   444.9 2647.73     461 2647.55
   492.4 2651.95     525 2653.93   544.6 2656.68   561.8 2659.83   574.8 2662.97
#Mann= 3 ,0,0
       0      .1       0   246.2    .045       0   286.7      .1       0
Bank Sta=246.2,286.7
XS Rating Curve= 0 ,0
Exp/Cntr=0.3,0.1
LCMann Table=0

Chan Stop Cuts=-1
Use User Specified Reach Order=0
Composite Channel Slope=5